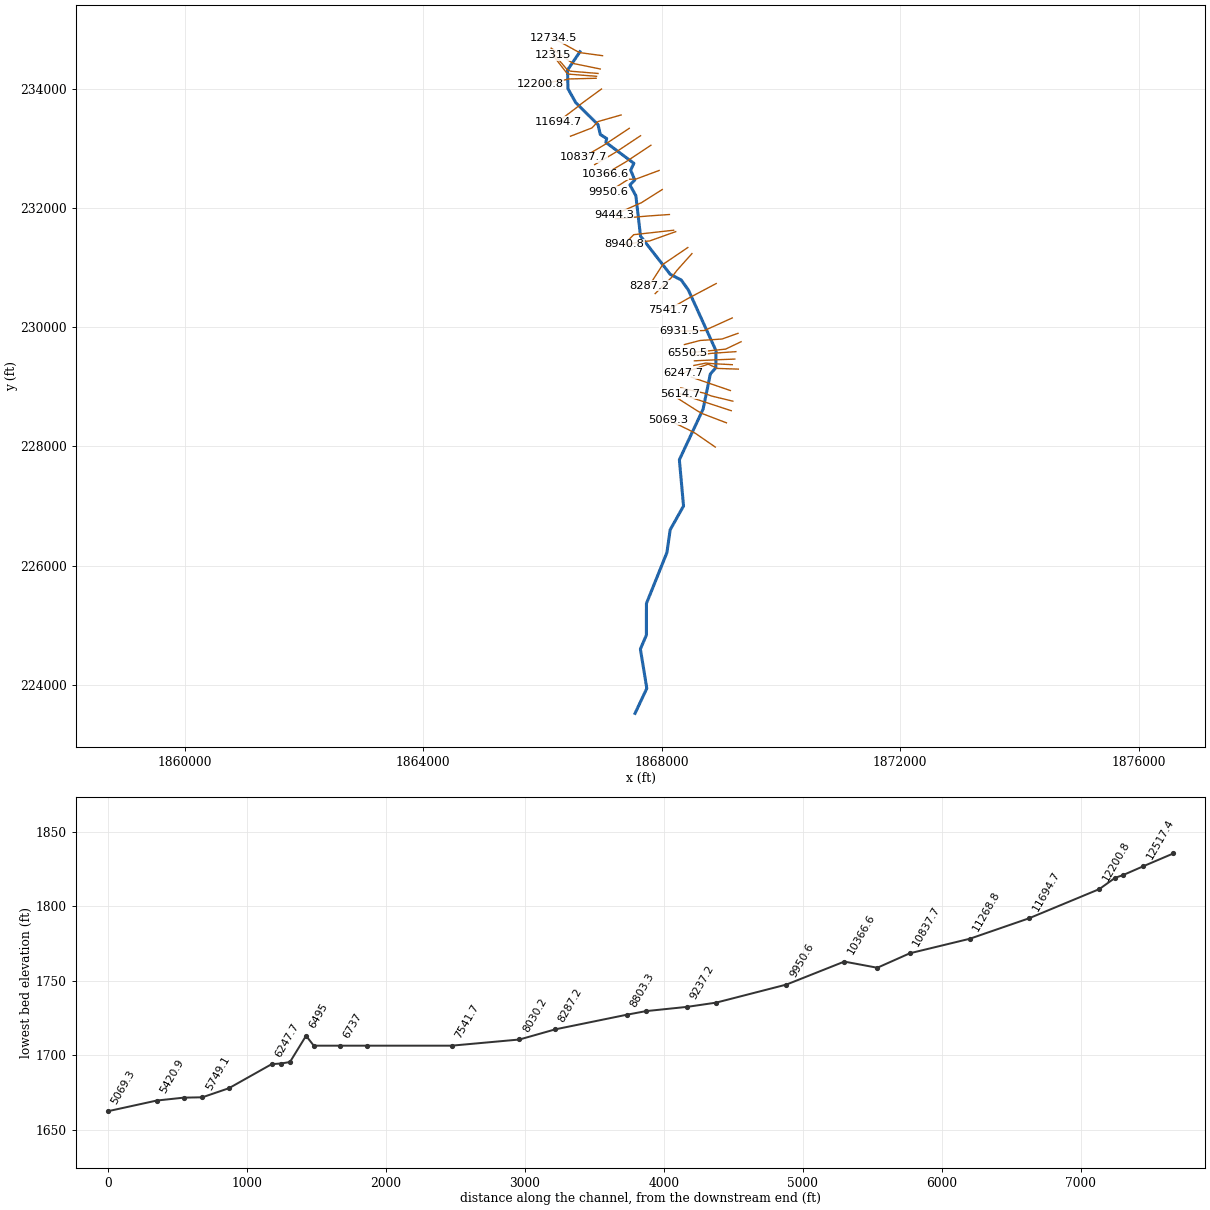
--- LtFkAllnCr.prj (project) ---

Proj Title=LtFkAllnCr
Current Plan=p01
Default Exp/Contr=0,0
English Units
Geom File=g01
Flow File=f01
Plan File=p01
BEGIN DESCRIPTION:
END DESCRIPTION:
DSS Export Rating Curves= 0
DSS Export Rating Curve Sorted= 0
DSS Export Volume Flow Curves= 0
DXF OffsetX= 0
DXF OffsetY= 0
DXF ScaleX= 0
DXF ScaleY= 0

--- LtFkAllnCr.p01 (plan) ---

Plan Title=Floodplain
Program Version=4.00
Geom File=g01
Flow File=f01
K Sum by GR=0
Std Step Tol=0.01
Critical Tol=0.01
Num of Std Step Trials=20
Max Error Tol=0.3
Flow Tol Ratio=0.001
Split Flow NTrial=30
Split Flow Tol=0.02
Split Flow Ratio=0.02
Log Output Level=0
Friction Slope Method=1
Unsteady Friction Slope Method=2
Unsteady Bridges Friction Slope Method=1
Global Log Level=0
CheckData=False
Run HTab=0
Run UNet=0
Run PostProcess=0
UNET Theta=0
UNET Theta Warmup=0
UNET ZTol=0
UNET ZSATol=0
UNET MxIter=0
UNET MaxInSteps=0
UNET DtIC=0
UNET DtMin=0
UNET MaxCRTS=0
UNET WFStab=0
UNET SFStab=0
UNET WFX=0
UNET SFX=0
UNET DSS MLevel=0
UNET DZMax Abort=0
UNET Convert EG Bridges=0
UNET Use Existing IB Tables=0
UNET Froude Limit=0
UNET Froude Power=0
Write IC File=0
Echo Input=False
Echo Output=False
Write Detailed=0

--- LtFkAllnCr.f01 (steady flow) ---

Flow Title=NFF Regression Equation
Program Version=4.00
Number of Profiles=1
Profile Names=P100yr
River Rch & RM=LtFkAllnCr,Main      ,12734.5
156.9633
River Rch & RM=LtFkAllnCr,Main      ,12517.4
161.1052
River Rch & RM=LtFkAllnCr,Main      ,12200.8
311.8053
River Rch & RM=LtFkAllnCr,Main      ,11268.8
340.2852
River Rch & RM=LtFkAllnCr,Main      ,9950.6
371.7557
River Rch & RM=LtFkAllnCr,Main      ,9950.6
432.8830
River Rch & RM=LtFkAllnCr,Main      ,8287.2
457.8023
River Rch & RM=LtFkAllnCr,Main      ,8287.2
499.9160
River Rch & RM=LtFkAllnCr,Main      ,7541.7
531.1557
River Rch & RM=LtFkAllnCr,Main      ,6931.5
582.2058
River Rch & RM=LtFkAllnCr,Main      ,5420.9
634.1475
River Rch & RM=LtFkAllnCr,Main      ,4206
687.1129
River Rch & RM=LtFkAllnCr,Main      ,3019.5
737.9368
River Rch & RM=LtFkAllnCr,Main      ,352.4
791.2386
Boundary for River Rch & Prof#=LtFkAllnCr,Main      ,1
Up Type=0
Dn Type=3
Dn Slope=0.006649

--- LtFkAllnCr.g01 (geometry) ---

Geom Title=USGS 10m DEM
Program Version=4.00

River Reach=LtFkAllnCr      ,Main
Reach XY= 30
     1866630.301        234619.4     1866421.721      234312.324
     1866428.964      233998.006     1866559.326       233766.25
     1866933.191      233395.718     1866970.692      233231.764
     1867077.879      233163.686     1867064.843      233098.505
     1867534.148      232747.974     1867480.554      232633.545
     1867548.632      232466.971     1867467.518      232385.857
     1867567.463      232204.798      1867645.68      231526.913
     1868143.954      230886.689     1868328.294      230790.852
     1868447.892      230623.791     1868912.014      229603.072
     1868908.195      229320.014     1868816.361      229214.482
     1868695.001      228625.617     1868297.251      227777.061
     1868366.798      227001.201     1868143.203      226601.956
     1868088.343      226219.435       1867744.9      225366.804
     1867743.851      224835.961     1867643.415      224602.209
     1867750.986      223942.481     1867553.563      223523.088

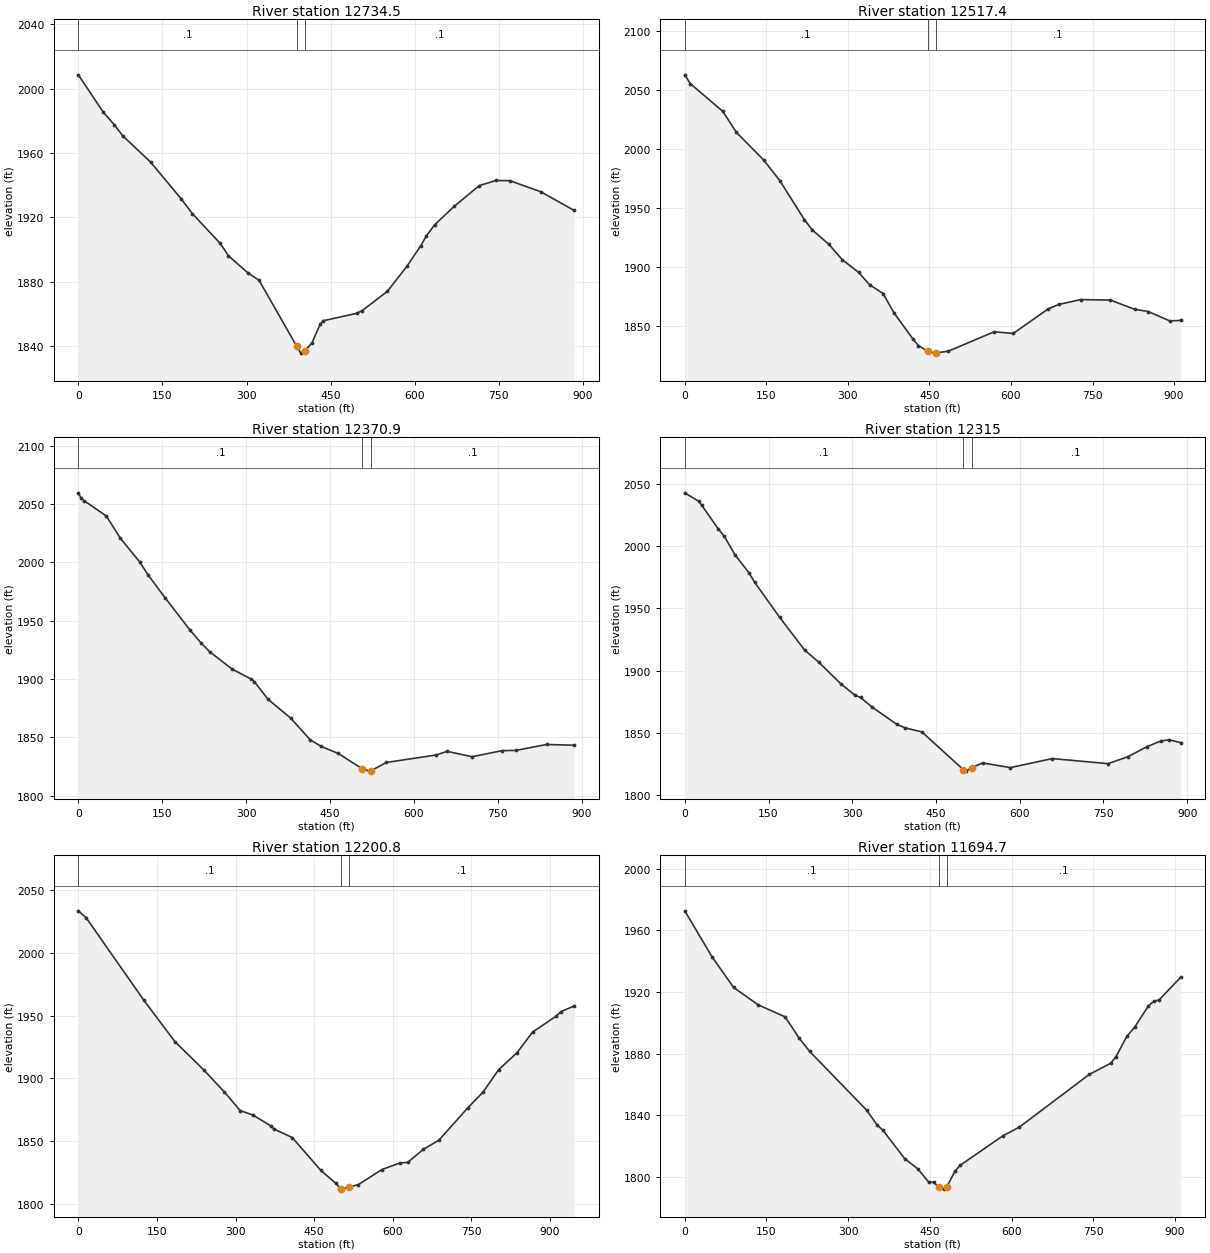
Type RM Length L Ch R = 1 ,12734.5 ,218.3,217.1,217.7
XS GIS Cut Line= 4
     1867008.574      234552.976     1866620.284      234605.316
     1866550.362      234643.513     1866189.392      234843.889
#Sta/Elev= 30
       0 2008.61    44.6 1985.31    64.5 1977.46    79.4 1970.62     129 1954.33
   183.5 1931.49   203.3 1922.34   252.9 1903.88   267.8 1896.07   302.5 1885.45
   322.4 1880.85   389.1 1840.08   396.8 1835.59   404.1    1837   416.7 1841.99
   431.6 1853.72   436.6 1855.71   496.4 1860.33   506.3 1862.04   551.1 1873.98
   585.9 1889.52   610.8 1902.36   620.7  1908.5   635.6 1915.39   670.4 1926.87
   715.2 1939.76   745.1 1942.93   769.9 1942.77   824.6 1935.95   884.3  1924.3
#Mann= 3 , 0 , 0
       0      .1       0   389.1    .045       0   404.1      .1       0
Bank Sta=389.1,404.1
XS Rating Curve= 0 ,0
Exp/Cntr=0.3,0.1

Type RM Length L Ch R = 1 ,12517.4 ,153,146.4,144.4
XS GIS Cut Line= 4
      1866970.45      234329.715     1866524.952      234421.005
      1866460.44      234458.739     1866147.617      234679.053
#Sta/Elev= 30
       0 2062.74      10 2055.35      70 2031.74      95 2013.94   144.9 1990.69
   174.9 1973.03   219.9 1940.12   234.9 1931.13   264.9 1919.19   289.8 1906.08
   319.8 1895.35   339.8 1884.93   364.8 1877.46   384.8 1861.07   419.8 1838.87
   429.8 1833.38   446.7 1828.58   459.7 1826.96   461.7 1827.13   484.6 1828.56
   569.2 1845.07     604 1843.59   668.6 1864.45   688.5 1868.29   728.3  1872.3
   782.9 1871.91   827.6 1864.07   852.5 1862.22   892.2 1854.25   912.1 1854.68
#Mann= 3 , 0 , 0
       0      .1       0   446.7    .045       0   461.7      .1       0
Bank Sta=446.7,461.7
XS Rating Curve= 0 ,0
Exp/Cntr=0.3,0.1

Type RM Length L Ch R = 1 ,12370.9 ,55.7,55.9,48.6
XS GIS Cut Line= 4
     1866933.755      234254.908     1866471.126      234292.973
      1866411.59      234323.229     1866181.251      234593.584
#Sta/Elev= 30
       0 2059.46       5 2054.93      10  2052.8    49.9 2039.69    74.9 2020.68
   109.8  2000.2   124.8 1989.07   154.7 1969.72   199.6 1941.88   219.6  1930.7
   234.6 1923.37   274.5 1908.54   309.5 1899.69   314.4 1897.74   339.4 1882.44
   379.3 1866.49   414.3 1847.94   434.2  1842.1   464.2 1836.26   507.8  1822.9
   521.4 1820.99   522.8 1821.25   550.7 1828.43   639.5 1834.82   659.2 1837.94
   703.6 1833.34   757.9 1838.57   782.6 1838.78   836.8 1843.83   886.2 1843.19
#Mann= 3 , 0 , 0
       0      .1       0   507.8    .045       0   522.8      .1       0
Bank Sta=507.8,522.8
XS Rating Curve= 0 ,0
Exp/Cntr=0.3,0.1

Type RM Length L Ch R = 1 ,12315   ,98.3,114.2,140.7
XS GIS Cut Line= 4
      1866908.18      234207.291     1866449.883      234242.898
     1866406.236      234264.722     1866173.067       234564.51
#Sta/Elev= 30
       0  2042.8      25    2036      30 2033.06      60 2013.75      70  2008.4
    89.9 1993.04   114.9 1978.57   124.9  1971.1   169.9  1942.8   214.8  1916.4
   239.8 1906.84   279.8 1889.25   304.8 1880.26   314.8 1878.41   334.8 1870.92
   379.7 1856.82   394.7 1853.99   424.7 1850.73   498.8 1820.51   503.6 1819.22
   513.8 1821.97   533.5 1825.79   583.4 1822.03   658.4  1829.3   758.3 1825.23
   793.3  1830.7   828.3 1838.92   853.3 1843.49   868.3 1844.41   888.3  1842.1
#Mann= 3 , 0 , 0
       0      .1       0   498.8    .045       0   513.8      .1       0
#XS Ineff= 2 , 0
                          539.42         1825.07
Permanent Ineff=
       F       F
Bank Sta=498.8,513.8
XS Rating Curve= 0 ,0
Exp/Cntr=0.3,0.1

Type RM Length L Ch R = 1 ,12200.8 ,495.8,506.1,516.4
XS GIS Cut Line= 4
     1866902.019      234174.304     1866439.249      234162.489
     1866365.199      234144.452     1865963.424      234080.421
#Sta/Elev= 30
       0 2033.76    14.9 2028.26   124.4 1962.73   184.2 1929.39   238.9 1906.94
   278.8  1889.1   308.6 1874.37   333.5 1870.69   368.4 1861.78   373.3 1859.57
   408.2 1852.77   462.9 1826.48   491.5 1816.18     501 1811.61   501.8 1811.62
   516.8 1813.34   534.4 1815.24   578.8 1827.16   613.6 1832.48   628.4 1832.94
   658.2 1843.34     688 1850.69   742.6 1876.29   772.3  1889.1   802.1 1907.05
   836.8 1920.39   866.6 1936.95   911.2 1949.57   921.2 1953.38     946 1957.82
#Mann= 3 , 0 , 0
       0      .1       0   501.8    .045       0   516.8      .1       0
Bank Sta=501.8,516.8
XS Rating Curve= 0 ,0
Exp/Cntr=0.3,0.1

Type RM Length L Ch R = 1 ,11694.7 ,423.4,425.8,428.3
XS GIS Cut Line= 4
     1866990.701       233994.61     1866652.966      233747.319
     1866586.261      233691.733     1866262.733      233448.078
#Sta/Elev= 30
       0 1972.67    49.8  1942.9    89.7 1922.91   134.6 1911.67   184.4  1903.8
   209.3 1890.35   229.2 1881.41   333.9 1843.26   353.8 1833.36   363.8 1830.22
   403.6 1811.88   428.2 1805.05   447.5 1796.71   457.2  1796.4   466.1  1793.4
   476.5    1792   481.1 1793.39   495.8 1803.53   505.4 1807.42   584.4 1826.69
   614.1  1832.2   742.5 1866.42     782 1873.72   791.9  1878.1   811.6 1891.16
   826.5 1897.38   851.2 1910.92     861 1913.92   870.9 1914.86   910.4 1929.48
#Mann= 3 , 0 , 0
       0      .1       0   466.1    .045       0   481.1      .1       0
Bank Sta=466.1,481.1
XS Rating Curve= 0 ,0
Exp/Cntr=0.3,0.1

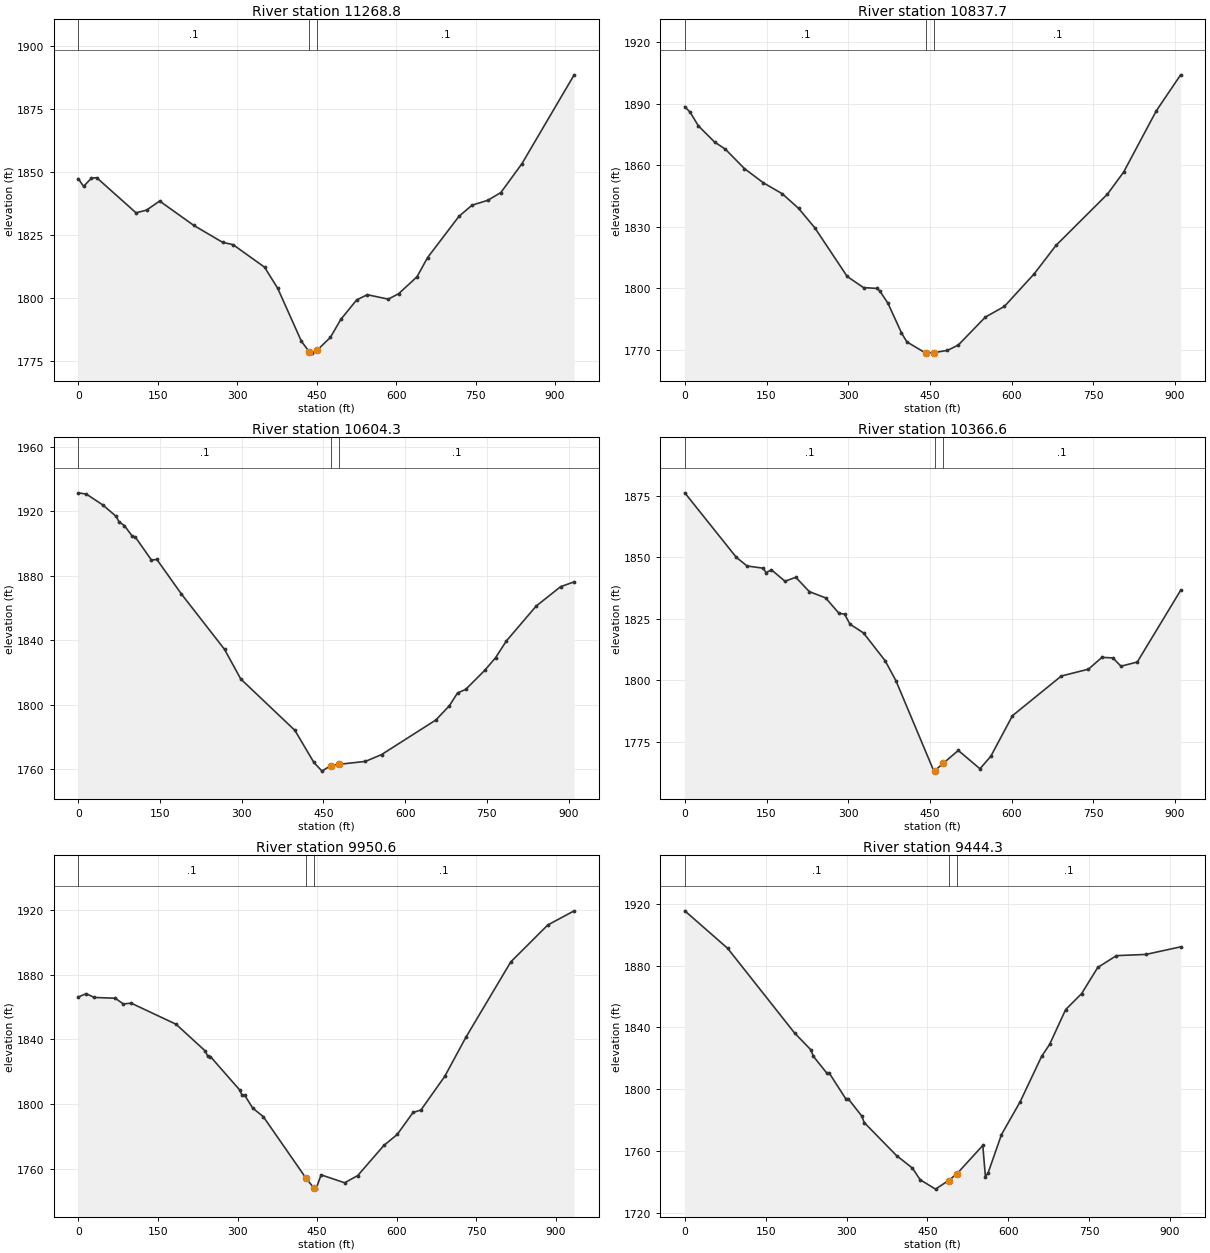
Type RM Length L Ch R = 1 ,11268.8 ,436.9,431.2,425.3
XS GIS Cut Line= 4
     1867320.423      233558.874     1866934.606      233449.003
     1866830.844      233341.535     1866471.219      233202.106
#Sta/Elev= 30
       0 1847.37     9.9 1844.35    24.8 1847.62    34.7 1847.78     109 1833.87
   128.8 1834.94   153.5 1838.54   217.9  1828.9   272.4 1822.18   292.2 1821.25
   351.6 1812.34   376.4 1803.98   421.1 1783.03   436.3 1778.71     441 1778.28
   451.3 1779.52   475.8 1784.49   495.8  1791.7   525.6 1799.38   545.6 1801.42
   585.2 1799.67   604.9 1801.84   639.6 1808.56   659.3  1816.1   718.7 1832.48
   743.4  1836.9   773.1 1838.82   797.8 1841.91   837.4 1853.27   936.2 1888.54
#Mann= 3 , 0 , 0
       0      .1       0   436.3    .045       0   451.3      .1       0
Bank Sta=436.3,451.3
XS Rating Curve= 0 ,0
Exp/Cntr=0.3,0.1

Type RM Length L Ch R = 1 ,10837.7 ,233.4,233.4,233.3
XS GIS Cut Line= 3
     1867457.174      233335.161     1867038.983      233057.343
     1866687.184      232850.169
#Sta/Elev= 30
       0 1888.47     9.9 1885.75    24.8 1879.18    54.7 1871.24    74.6 1867.77
   109.4 1858.36   144.2 1851.43     179 1846.08   208.8 1839.01   238.6 1829.56
   298.2 1805.83   328.1 1800.42   352.9 1800.02   357.9  1798.8   372.8  1792.9
   397.7 1778.46   407.6 1774.01   442.4 1768.53   442.8 1768.53   457.8 1768.81
   482.2 1769.86   502.1 1772.46   551.8 1786.07   586.7 1791.25   641.5 1807.13
   681.3 1820.91   775.9 1845.89   805.8 1856.69   865.5 1886.38   910.3 1903.97
#Mann= 3 , 0 , 0
       0      .1       0   442.8    .045       0   457.8      .1       0
Bank Sta=442.8,457.8
XS Rating Curve= 0 ,0
Exp/Cntr=0.3,0.1

Type RM Length L Ch R = 1 ,10604.3 ,238.2,237.7,237.3
XS GIS Cut Line= 3
      1867646.42      233210.772      1867228.23      232932.954
     1866876.431      232725.781
#Sta/Elev= 30
       0 1931.31    14.9  1930.5    44.7 1923.86    69.6 1916.69    74.6 1913.37
    84.5 1911.01    99.4 1904.29   104.4 1904.02   134.2 1889.65   144.2 1890.02
   188.9 1868.76   268.4  1834.3   298.2 1815.94   397.7 1784.06   432.5 1764.18
   447.4 1758.83   463.4 1762.29   478.4 1763.04     527 1764.86   556.8  1769.1
   656.4 1790.52   681.3  1799.4   696.2 1807.29   711.2  1809.5     746 1821.24
   765.9 1829.08   785.9 1839.52   840.6 1861.14   885.4 1873.13   910.3 1876.14
#Mann= 3 , 0 , 0
       0      .1       0   463.4    .045       0   478.4      .1       0
Bank Sta=463.4,478.4
XS Rating Curve= 0 ,0
Exp/Cntr=0.3,0.1

Type RM Length L Ch R = 1 ,10366.6 ,431.9,416,384.9
XS GIS Cut Line= 3
     1867819.405      233050.948     1867401.215       232773.13
     1867049.416      232565.957
#Sta/Elev= 30
       0 1876.21    94.4 1850.01   114.3 1846.44   144.2 1845.54   149.1 1843.71
   159.1 1844.88   183.9 1840.24   203.8 1841.83   228.7 1835.99   258.5 1833.47
   283.3 1827.12   293.3 1826.89   303.2 1822.78   328.1 1819.19   367.8 1807.89
   387.7 1799.73   457.3 1762.96   459.1 1763.15   474.1 1766.08   502.1 1771.37
   541.9 1763.93   561.8    1769   601.6 1785.53   691.3 1801.67     741 1804.44
   765.9 1809.26   785.9 1809.03   800.8 1805.66   830.7 1807.36   910.3 1836.52
#Mann= 3 , 0 , 0
       0      .1       0   459.1    .045       0   474.1      .1       0
Bank Sta=459.1,474.1
XS Rating Curve= 0 ,0
Exp/Cntr=0.3,0.1

Type RM Length L Ch R = 1 ,9950.6  ,496.5,506.3,515.9
XS GIS Cut Line= 4
     1867957.406      232628.169      1867570.15      232483.643
       1867442.3      232479.937     1867110.631      232268.707
#Sta/Elev= 30
       0 1866.15    14.9 1868.19    29.9 1865.84    69.7 1865.36    84.7 1861.83
    99.6 1862.33   184.3 1849.29     239 1832.88     244 1829.54     249 1829.34
   303.8 1808.86   308.8 1805.42   313.7 1805.39   328.7 1797.53   348.6 1792.29
   429.2 1754.27   444.2 1748.14   447.8 1747.54   457.6 1756.34   501.9 1751.47
   526.5 1755.88   576.1 1774.58     601 1781.28   630.8 1794.84   645.8 1796.41
   690.6 1817.15   730.4 1841.23     815 1887.77   884.7 1910.56   934.5 1919.31
#Mann= 3 , 0 , 0
       0      .1       0   429.2    .045       0   444.2      .1       0
Bank Sta=429.2,444.2
XS Rating Curve= 0 ,0
Exp/Cntr=0.3,0.1

Type RM Length L Ch R = 1 ,9444.3  ,214.2,207.1,199.8
XS GIS Cut Line= 4
     1868010.067      232308.314     1867657.236       232085.27
     1867573.856      232050.065      1867198.42      231881.478
#Sta/Elev= 30
       0 1915.46    79.5 1891.19   203.7 1836.37   233.6  1825.6   238.5 1821.32
   263.4 1810.46   268.3 1810.24   298.2 1794.03   303.1 1793.86     328 1782.78
   332.9  1778.4   392.6 1757.14   422.2 1748.99   436.5 1741.47     465  1735.4
   489.1 1740.98   504.1 1745.12   552.6 1763.66   557.5  1743.4   562.5 1745.94
   587.3 1770.71     622 1791.99   661.6 1821.21   676.5 1829.02   706.3 1851.58
     736 1861.95   765.8 1878.82   800.5 1886.47     855 1887.25   919.5 1892.16
#Mann= 3 , 0 , 0
       0      .1       0   489.1    .045       0   504.1      .1       0
Bank Sta=489.1,504.1
XS Rating Curve= 0 ,0
Exp/Cntr=0.3,0.1

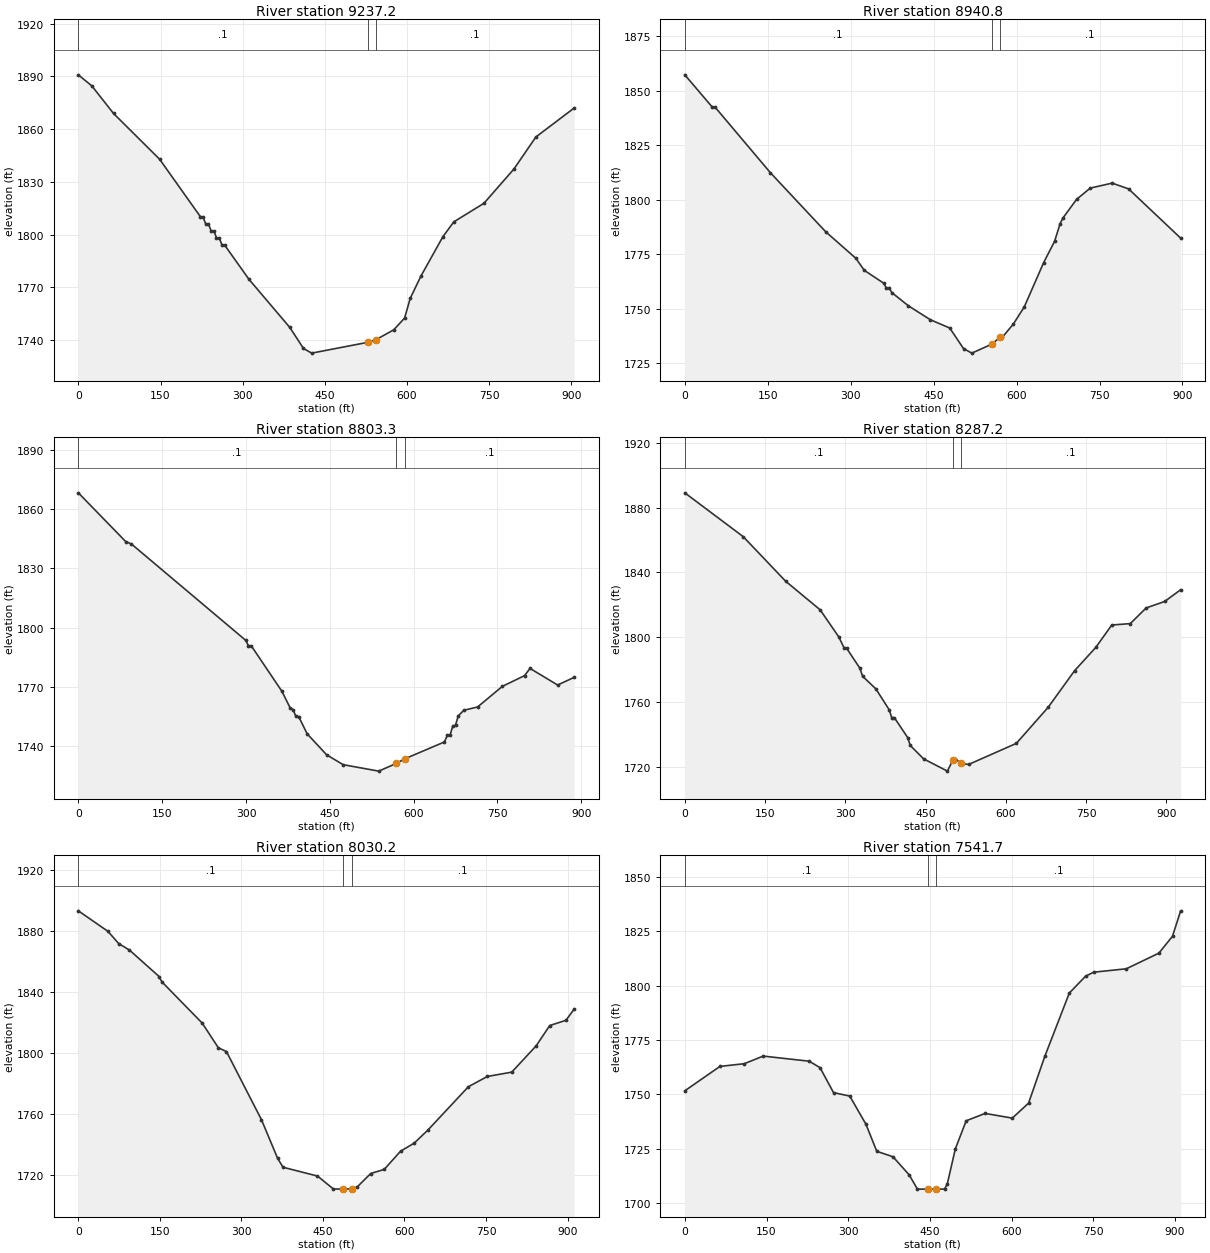
Type RM Length L Ch R = 1 ,9237.2  ,296,296.4,296.7
XS GIS Cut Line= 3
     1868130.306      231889.387     1867779.979      231865.266
     1867228.217      231816.495
#Sta/Elev= 30
       0 1890.93    24.7 1884.61    64.3 1868.93   148.4  1842.9   222.6 1810.31
   227.5 1810.09   232.5 1806.16   237.4 1806.13   242.4 1802.18   247.3 1802.15
   252.2 1798.21   257.2 1798.08   262.1 1794.28   267.1 1794.04   311.6 1774.53
   386.1 1747.17     411 1735.23     426 1732.58   528.4 1738.73   543.4 1740.24
   575.7 1745.83   595.7 1752.57   605.7 1763.67   625.6 1776.54   665.5 1798.84
   685.5  1807.3   740.4 1817.82   795.3  1837.4   835.2 1855.56   905.1 1872.04
#Mann= 3 , 0 , 0
       0      .1       0   528.4    .045       0   543.4      .1       0
Bank Sta=528.4,543.4
XS Rating Curve= 0 ,0
Exp/Cntr=0.3,0.1

Type RM Length L Ch R = 1 ,8940.8  ,137.9,137.5,137.1
XS GIS Cut Line= 3
     1868200.645      231625.864     1867531.006      231550.858
     1867375.277      231391.411
#Sta/Elev= 30
       0 1857.37    49.9  1842.5    54.9  1842.5   154.7  1812.5   254.6 1785.44
   309.5 1773.19   324.4 1767.73   359.4 1761.85   364.4 1759.68   369.4 1759.71
   374.4 1757.49   404.3 1751.43   444.2 1745.02   479.2 1741.23   504.1  1731.8
   519.1 1729.72   554.8  1733.8   569.8 1736.94     574 1736.94     594    1743
   613.9  1750.9   648.9 1771.19   668.8 1781.03   678.8 1789.14   683.7 1791.65
   708.5 1800.24   733.3 1805.42   772.9  1807.7   802.6 1805.05   896.7 1782.48
#Mann= 3 , 0 , 0
       0      .1       0   554.8    .045       0   569.8      .1       0
Bank Sta=554.8,569.8
XS Rating Curve= 0 ,0
Exp/Cntr=0.3,0.1

Type RM Length L Ch R = 1 ,8803.3  ,503.3,516.1,537.8
XS GIS Cut Line= 4
     1868235.341      231601.663     1867798.057       231446.02
     1867642.462      231430.114      1867380.54      231379.959
#Sta/Elev= 30
       0 1868.35    84.8 1843.64    94.8 1842.46   299.5  1793.6   304.4 1790.84
   309.4 1790.84   364.3 1767.75   379.3  1759.2   384.3  1758.5   389.3    1755
   394.3 1754.94   409.3 1746.28   444.2  1735.6   473.9 1730.58   537.5 1727.31
   568.7 1731.18   583.7 1733.49   655.1  1742.1   660.1 1745.38     665 1745.49
     670 1750.14   674.9 1750.61   679.8 1755.28   689.7 1758.14   714.4 1759.82
   758.8 1770.28   798.4  1775.7   808.2 1779.37   857.6 1770.95   887.2 1774.83
#Mann= 3 , 0 , 0
       0      .1       0   568.7    .045       0   583.7      .1       0
Bank Sta=568.7,583.7
XS Rating Curve= 0 ,0
Exp/Cntr=0.3,0.1

Type RM Length L Ch R = 1 ,8287.2  ,250.4,257,254.6
XS GIS Cut Line= 4
     1868438.615      231335.386       1868077.3      231090.803
      1868019.86      231051.893     1867791.953      230697.989
#Sta/Elev= 30
       0 1889.09   109.1 1862.09   188.4  1834.6   252.9 1816.95   287.6 1800.32
   297.5  1793.6   302.4 1793.25   327.2 1780.91   332.2    1776     357 1768.22
   381.8 1755.39   386.7 1750.48   391.7 1750.42   416.5 1738.15   421.4 1733.28
   446.2 1725.05   490.8 1717.46   500.6 1724.04   505.7 1725.15   515.6 1722.19
   530.4 1721.58   619.6 1734.57     679  1756.8   728.5 1779.42   768.2 1793.82
   797.9 1807.57   832.5 1808.44   862.2  1818.1   896.9  1822.1   926.6 1829.33
#Mann= 3 , 0 , 0
       0      .1       0   500.6    .045       0   515.6      .1       0
Bank Sta=500.6,515.6
XS Rating Curve= 0 ,0
Exp/Cntr=0.3,0.1

Type RM Length L Ch R = 1 ,8030.2  ,498.6,488.5,478.5
XS GIS Cut Line= 4
     1868508.137      231233.901      1868253.87      230949.443
     1868172.342      230840.122     1867891.752      230563.113
#Sta/Elev= 30
       0 1893.45    54.5 1879.97    74.3 1871.94    94.1 1867.67   148.6 1850.29
   153.6 1846.85   227.9  1819.7   257.7 1803.48   272.5 1801.03   336.9 1756.26
   366.7 1730.84   376.6 1725.03     440 1719.25   469.2 1710.77   483.8 1710.66
   487.8  1710.8   502.8 1710.79     513 1712.09   537.9 1720.91   562.8 1723.62
   592.8 1735.57   617.7 1740.81   642.7  1749.3   717.6 1777.92   752.5 1784.66
   797.4  1787.5   842.3 1804.78   867.3 1818.11   897.2 1821.57   912.2 1828.96
#Mann= 3 , 0 , 0
       0      .1       0   487.8    .045       0   502.8      .1       0
Bank Sta=487.8,502.8
XS Rating Curve= 0 ,0
Exp/Cntr=0.3,0.1

Type RM Length L Ch R = 1 ,7541.7  ,611.9,610.2,608.5
XS GIS Cut Line= 4
     1868914.909      230731.901     1868594.803      230562.188
     1868428.042      230473.249     1868116.289      230295.637
#Sta/Elev= 30
       0 1751.66    64.5 1762.87   109.2 1764.11   143.9 1767.61   228.3 1765.26
   248.2  1762.3     273 1750.83   302.8 1749.24   332.5 1736.31   352.4 1723.88
   382.2 1721.37     412 1713.02     427 1706.51     447 1706.51     462 1706.51
   476.7 1706.53   481.7 1708.78   496.6 1725.01   516.5  1737.9   551.3 1741.28
   601.1 1739.12     631 1746.01   660.9 1767.55   705.8 1796.57   735.7 1804.31
   750.6 1806.14   810.4  1807.7   870.2 1814.89   895.2 1822.64   910.1 1834.32
#Mann= 3 , 0 , 0
       0      .1       0     447    .045       0     462      .1       0
Bank Sta=447,462
XS Rating Curve= 0 ,0
Exp/Cntr=0.3,0.1

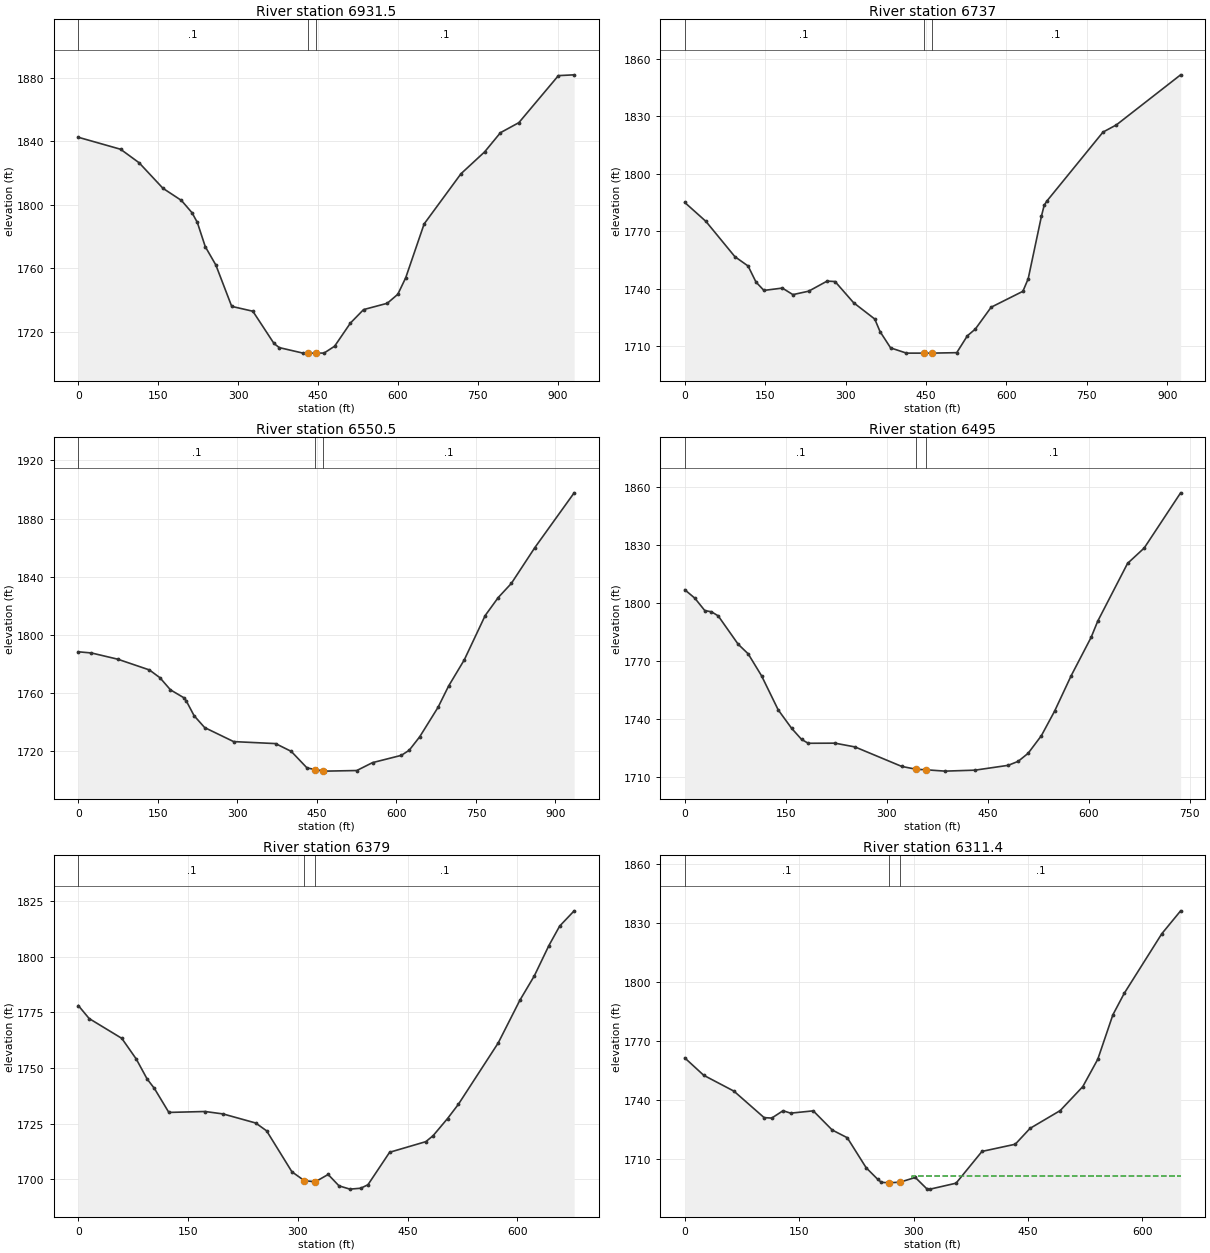
Type RM Length L Ch R = 1 ,6931.5  ,202.4,194.5,186.6
XS GIS Cut Line= 4
     1869184.024       230154.55      1868835.68      229997.054
     1868713.388       229943.32     1868298.339      229934.055
#Sta/Elev= 30
       0 1842.56    79.4    1835   114.2 1826.47   158.9  1810.4   193.6 1802.74
   213.5 1794.99   223.4 1788.92   238.3 1773.66   258.2 1762.06     288 1735.97
   327.7 1732.92   367.4 1712.58   377.3 1709.99   421.9 1706.51   430.7 1706.51
   445.7 1706.51   461.4 1706.55   481.2 1710.86   510.9 1725.47   535.6 1733.95
   580.1 1737.93   599.9 1743.61   614.7    1754   649.3 1787.94   718.5 1819.58
     763 1833.39   792.6 1845.45   827.2 1851.78   901.4 1881.42     931 1881.92
#Mann= 3 , 0 , 0
       0      .1       0   430.7    .045       0   445.7      .1       0
Bank Sta=430.7,445.7
XS Rating Curve= 0 ,0
Exp/Cntr=0.3,0.1

Type RM Length L Ch R = 1 ,6737    ,185.8,186.5,187.1
XS GIS Cut Line= 4
     1869280.484      229896.648     1869011.646      229801.061
     1868647.222      229777.164     1868381.371      229708.461
#Sta/Elev= 30
       0 1785.01    39.4 1775.17    93.5 1756.76   118.1 1751.91   132.8 1743.56
   147.6 1739.19     182 1740.41   201.7    1737   231.2  1738.8   265.6 1744.06
   280.4 1743.81   314.9 1732.79   354.4 1724.28   364.3 1717.73     384 1709.24
   413.6 1706.51   445.4 1706.51   460.4 1706.51   507.4 1706.75   527.2 1715.54
     542 1719.03   571.6 1730.44   630.8 1738.73   640.7 1745.26   665.5 1777.98
   670.5 1783.52   675.5 1785.75   780.3  1821.7   805.3 1825.46   925.1 1851.54
#Mann= 3 , 0 , 0
       0      .1       0   445.4    .045       0   460.4      .1       0
Bank Sta=445.4,460.4
XS Rating Curve= 0 ,0
Exp/Cntr=0.3,0.1

Type RM Length L Ch R = 1 ,6550.5  ,57,55.6,53.7
XS GIS Cut Line= 4
      1869332.65      229756.167     1869072.851      229632.033
     1868674.477      229591.269     1868428.275      229574.312
#Sta/Elev= 30
       0  1788.5    24.8 1787.69    74.5  1783.4     134 1776.04   153.9 1770.69
   173.8 1762.35   198.6 1757.02   203.5 1754.84   218.4 1744.56   238.3 1736.43
   292.9  1726.8     372 1725.43   401.6 1720.08   431.3 1708.72   447.3 1707.56
   462.3 1706.56   465.9 1706.51   525.2 1706.92   554.9 1712.35   609.3 1717.36
   624.1 1720.87   643.9 1730.11   678.5 1750.37   698.3 1764.93   727.9 1782.92
   767.4 1813.42     792 1825.78   816.7 1835.47   861.1 1860.12   935.2 1897.72
#Mann= 3 , 0 , 0
       0      .1       0   447.3    .045       0   462.3      .1       0
Bank Sta=447.3,462.3
XS Rating Curve= 0 ,0
Exp/Cntr=0.3,0.1

Type RM Length L Ch R = 1 ,6495    ,116.9,116,115.3
XS GIS Cut Line= 3
     1869244.242      229589.508     1868829.065      229560.419
     1868511.732      229518.108
#Sta/Elev= 30
       0 1806.99    14.9 1802.64    29.7 1796.22    39.6 1795.59    49.6 1793.48
    79.3 1778.79    94.1 1773.85     114 1762.47   138.7 1744.85   158.6 1735.33
   173.4 1729.57   183.3 1727.57     223 1727.63   252.7 1725.68   322.1  1715.6
   343.7 1714.11   358.7 1713.84   386.5 1713.16     431 1713.66   480.2 1716.16
     495 1718.21   509.8 1722.37   529.5 1731.49   549.2 1744.23   573.8 1762.56
   603.4 1782.37   613.2 1790.74   657.5 1820.63   682.2 1828.58   736.3 1857.14
#Mann= 3 , 0 , 0
       0      .1       0   343.7    .045       0   358.7      .1       0
Bank Sta=343.7,358.7
XS Rating Curve= 0 ,0
Exp/Cntr=0.3,0.1

Type RM Length L Ch R = 1 ,6379    ,69.6,67.6,65.5
XS GIS Cut Line= 3
     1869226.449      229464.761     1868885.316      229451.539
     1868549.472      229435.672
#Sta/Elev= 30
       0 1778.03    14.8 1772.18    59.4 1763.28    79.2 1753.97      94 1745.02
   103.9 1740.79   123.7 1729.99   173.2  1730.4   197.9  1729.3   242.4 1725.23
   257.3 1721.71   291.9  1703.3     309 1699.28     324 1698.83   341.4  1702.1
   356.2 1696.99   371.1 1695.51   385.9 1695.91   395.8 1697.48   425.4 1712.07
   474.9 1716.85   484.8 1719.52   504.6 1727.25   519.4 1733.65   573.8 1761.21
   603.4  1780.4   623.2 1791.39     643 1804.95   657.8 1813.75   677.6  1820.6
#Mann= 3 , 0 , 0
       0      .1       0     309    .045       0     324      .1       0
#XS Ineff= 2 , 0
                          341.42         1702.07
Permanent Ineff=
       F       F
Bank Sta=309,324
XS Rating Curve= 0 ,0
Exp/Cntr=0.3,0.1

Type RM Length L Ch R = 1 ,6311.4  ,72.4,63.7,54.7
XS GIS Cut Line= 4
     1869184.726      229370.737     1868877.971      229386.604
     1868737.816      229397.182     1868539.483      229357.515
#Sta/Elev= 30
       0 1761.25    24.8 1752.42    64.4 1744.36     104 1730.88     114 1730.66
   128.8  1734.4   138.7 1733.16   168.4 1734.33   193.2  1724.6     213 1720.66
   237.8 1705.37   252.7  1699.6   257.6 1698.01   267.4  1697.7   282.4 1698.09
   282.4  1698.1   302.2 1700.45   316.9 1694.83   321.7 1694.52   355.6 1697.54
   389.6  1713.7   433.2 1717.35   452.6 1725.42   492.1 1734.46   521.7 1746.63
   541.4 1760.57   561.2 1783.19     576 1794.05   625.3  1824.4     650 1836.06
#Mann= 3 , 0 , 0
       0      .1       0   267.4    .045       0   282.4      .1       0
#XS Ineff= 2 , 0
                          298.23         1701.11
Permanent Ineff=
       F       F
Bank Sta=267.4,282.4
XS Rating Curve= 0 ,0
Exp/Cntr=0.3,0.1

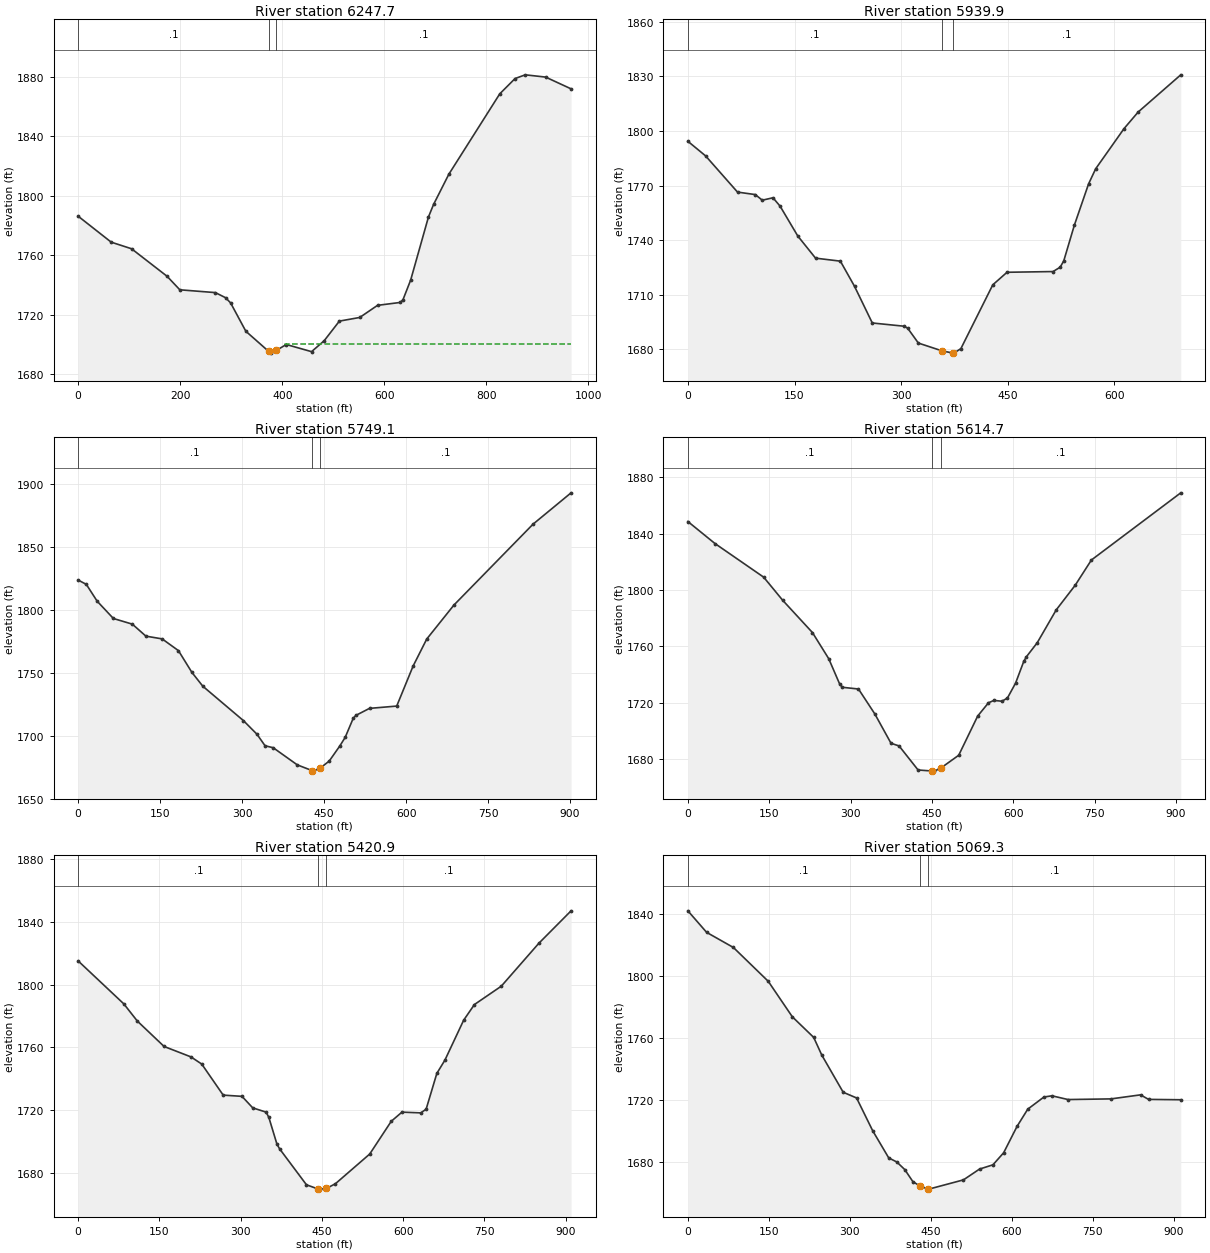
Type RM Length L Ch R = 1 ,6247.7  ,305.7,307.8,310.1
XS GIS Cut Line= 4
     1869285.934      229296.658     1868937.589      229307.776
     1868780.093      229380.039     1868361.338      229231.807
#Sta/Elev= 30
       0 1786.18    64.7 1768.74   104.6  1764.3   174.3 1745.77   199.2  1736.7
   268.9 1734.81   288.8 1731.39   298.7  1727.9   328.6 1708.82   373.3 1695.29
   373.3 1695.28   378.2 1694.11   388.3 1695.93   407.9 1699.91   457.4  1695.1
   482.2 1702.48   511.9 1715.64   551.8  1718.1   586.7 1726.25   631.6 1728.21
   636.6 1730.07   651.6 1743.22   686.5 1785.68   696.5 1794.09   726.4  1814.4
   826.3 1868.51   856.2 1878.77   876.2 1881.27   916.1 1879.75     966 1871.84
#Mann= 3 , 0 , 0
       0      .1       0   373.3    .045       0   388.3      .1       0
#XS Ineff= 2 , 0
                          404.78         1700.13
Permanent Ineff=
       F       F
Bank Sta=373.3,388.3
XS Rating Curve= 0 ,0
Exp/Cntr=0.3,0.1

Type RM Length L Ch R = 1 ,5939.9  ,191.7,190.8,189.9
XS GIS Cut Line= 2
     1869152.993      228937.049     1868497.172      229161.826
#Sta/Elev= 30
       0 1794.31    24.9  1786.3    69.8 1766.41    94.8 1765.04   104.7 1761.95
   119.7 1763.29   129.7 1758.68   154.6 1742.27   179.6 1730.12   214.5 1728.47
   234.4 1714.65   259.4 1694.51   304.2 1692.73   309.2 1691.62   324.2 1683.48
   358.1 1679.11   373.1    1678   374.1 1677.95     384 1680.42   428.9 1715.48
   448.9 1722.36   513.7 1722.76   523.7 1725.17   528.7 1728.61   543.6 1748.21
   563.6 1770.88   573.6 1779.21   613.5 1801.28   633.4  1810.4   693.3 1830.82
#Mann= 3 , 0 , 0
       0      .1       0   358.1    .045       0   373.1      .1       0
Bank Sta=358.1,373.1
XS Rating Curve= 0 ,0
Exp/Cntr=0.3,0.1

Type RM Length L Ch R = 1 ,5749.1  ,133,134.4,135.7
XS GIS Cut Line= 4
     1869193.289      228759.318     1868831.974      228846.404
     1868709.683       228894.58     1868320.574      228981.666
#Sta/Elev= 30
       0 1823.68    14.9 1820.25    34.7  1806.9    64.4 1793.15    99.1 1788.64
   123.9 1779.12   153.6 1776.94   183.4 1767.62   208.1 1750.29     228 1739.34
   302.3 1712.01   327.1 1701.18   341.9 1692.02   356.8 1690.46   400.9 1676.82
   427.8 1672.31   430.1 1671.86   442.8 1674.29   459.3 1679.85   478.8 1691.93
   488.5 1698.68   503.1 1713.72   508.1 1716.16     533 1721.72   582.8 1723.55
   612.8 1755.37   637.7 1776.81   687.5 1803.83   832.1 1868.05   901.8    1893
#Mann= 3 , 0 , 0
       0      .1       0   427.8    .045       0   442.8      .1       0
Bank Sta=427.8,442.8
XS Rating Curve= 0 ,0
Exp/Cntr=0.3,0.1

Type RM Length L Ch R = 1 ,5614.7  ,197.9,193.8,189.8
XS GIS Cut Line= 2
     1869166.855       228599.08     1868303.207      228882.356
#Sta/Elev= 30
       0  1848.5    49.9 1832.92   139.8 1809.06   174.8  1792.7   229.7 1769.82
   259.7 1751.31   279.7 1733.51   284.7 1731.04   314.6 1729.81   344.6 1712.23
   374.6 1691.36   389.5 1689.46   424.5 1672.43     451 1671.68   454.5 1671.62
     466 1673.68   499.4 1682.86   534.4 1710.65   554.3 1720.05   564.3 1721.72
   579.3 1721.16   589.3 1723.46   604.3 1733.99   619.3 1749.31   624.3 1752.69
   644.2 1762.59   679.2 1785.87   714.2 1803.33   744.1 1821.23   908.9 1868.84
#Mann= 3 , 0 , 0
       0      .1       0     451    .045       0     466      .1       0
Bank Sta=451,466
XS Rating Curve= 0 ,0
Exp/Cntr=0.3,0.1

Type RM Length L Ch R = 1 ,5420.9  ,351.4,351.5,351.7
XS GIS Cut Line= 4
     1869085.821       228396.15     1868687.448      228548.088
     1868602.214       228594.41     1868276.104      228801.934
#Sta/Elev= 30
       0  1815.1    84.3 1787.72   109.1 1776.82   158.6 1760.59   208.2 1753.95
   228.1 1749.38   267.7 1729.59   302.4 1728.81   322.2 1721.47     347 1718.74
     352 1715.35   366.9 1698.38   371.8 1695.37   421.4 1672.45   443.3  1669.7
   445.8 1669.68   458.3 1670.12   474.9 1673.13   538.2 1692.05   577.9 1712.89
   597.7 1718.75   632.4 1718.28   642.3  1720.6   662.1 1743.44     677 1751.89
   711.7  1777.4   731.5 1787.32   781.1 1799.02   850.4 1826.36   909.9 1847.04
#Mann= 3 , 0 , 0
       0      .1       0   443.3    .045       0   458.3      .1       0
Bank Sta=443.3,458.3
XS Rating Curve= 0 ,0
Exp/Cntr=0.3,0.1

Type RM Length L Ch R = 1 ,5069.3  ,304.8,309,313.3
XS GIS Cut Line= 4
     1868899.691      227989.053     1868565.157      228220.124
     1868455.836      228277.564     1868111.518      228444.421
#Sta/Elev= 30
       0 1841.93    34.7 1828.05    84.3 1818.29   148.8  1796.5   193.4 1773.61
     233 1760.31   247.9 1748.95   287.6 1724.95   312.4 1721.28   342.1 1700.22
   371.9 1682.64   386.8 1680.01   401.6 1675.12   416.5 1667.39   429.4 1664.55
   444.4 1662.58   446.1  1662.5   510.3 1668.47     540 1675.42   564.9 1678.18
   584.7 1685.94   609.6 1703.01   629.4 1714.07   659.3 1721.89   674.2 1722.67
     704 1720.25   783.5 1720.68   838.2 1723.28   853.1 1720.35   912.7 1720.12
#Mann= 3 , 0 , 0
       0      .1       0   429.4    .045       0   444.4      .1       0
Bank Sta=429.4,444.4
XS Rating Curve= 0 ,0
Exp/Cntr=0.3,0.1