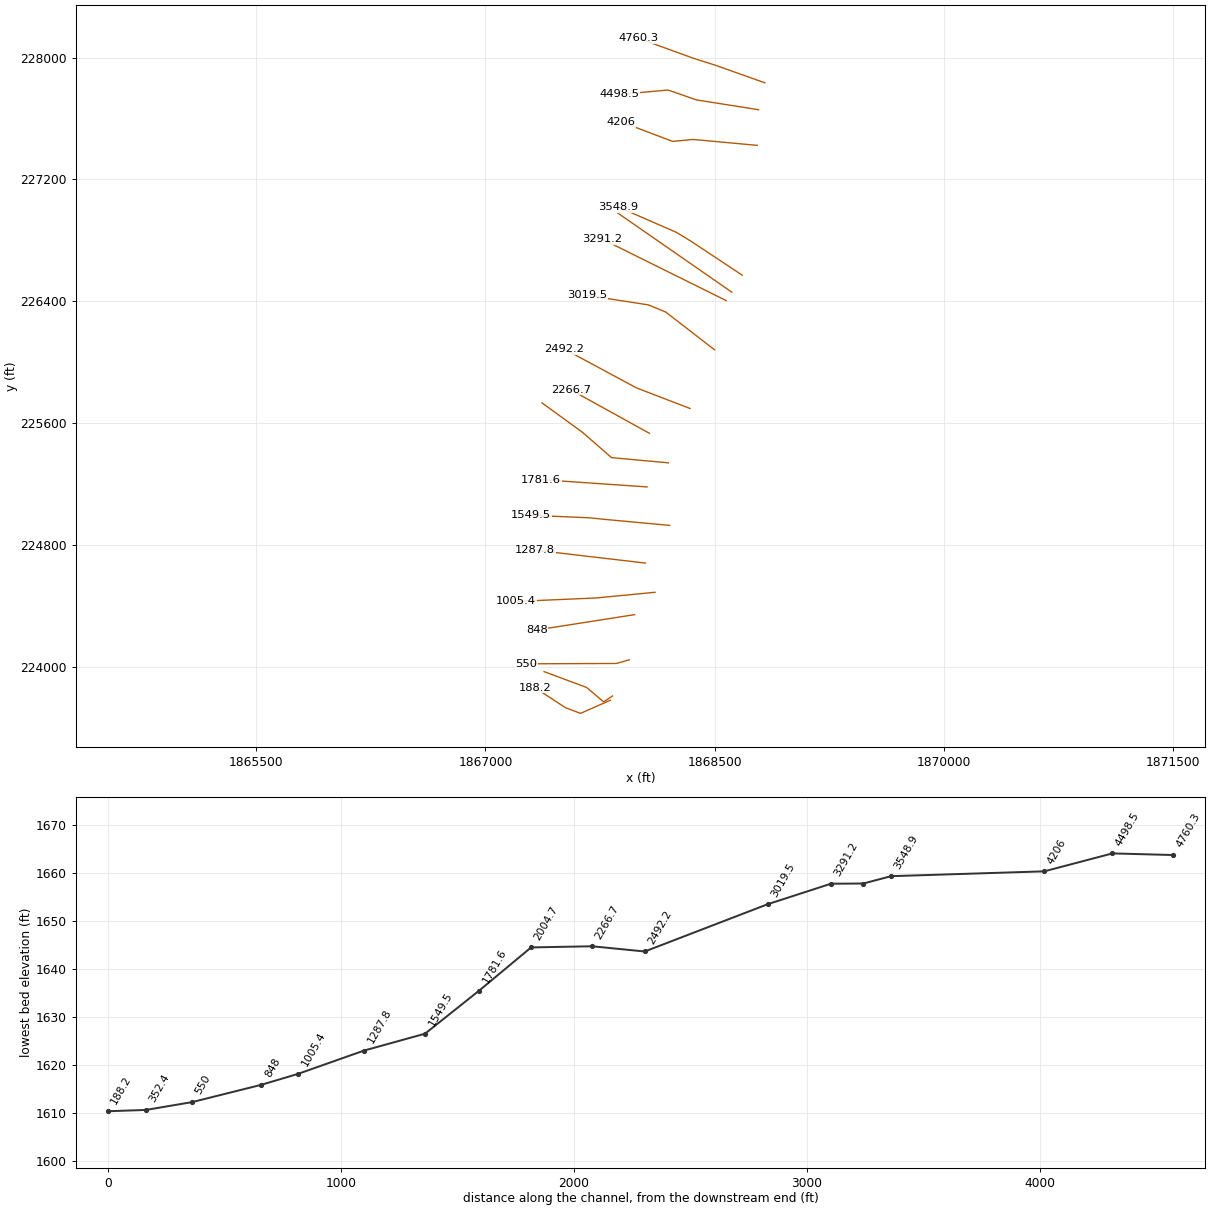
HEC-RAS study LtFkAllnCr.prj: LtFkAllnCr

--- LtFkAllnCr.g01 (geometry) --- (continued)

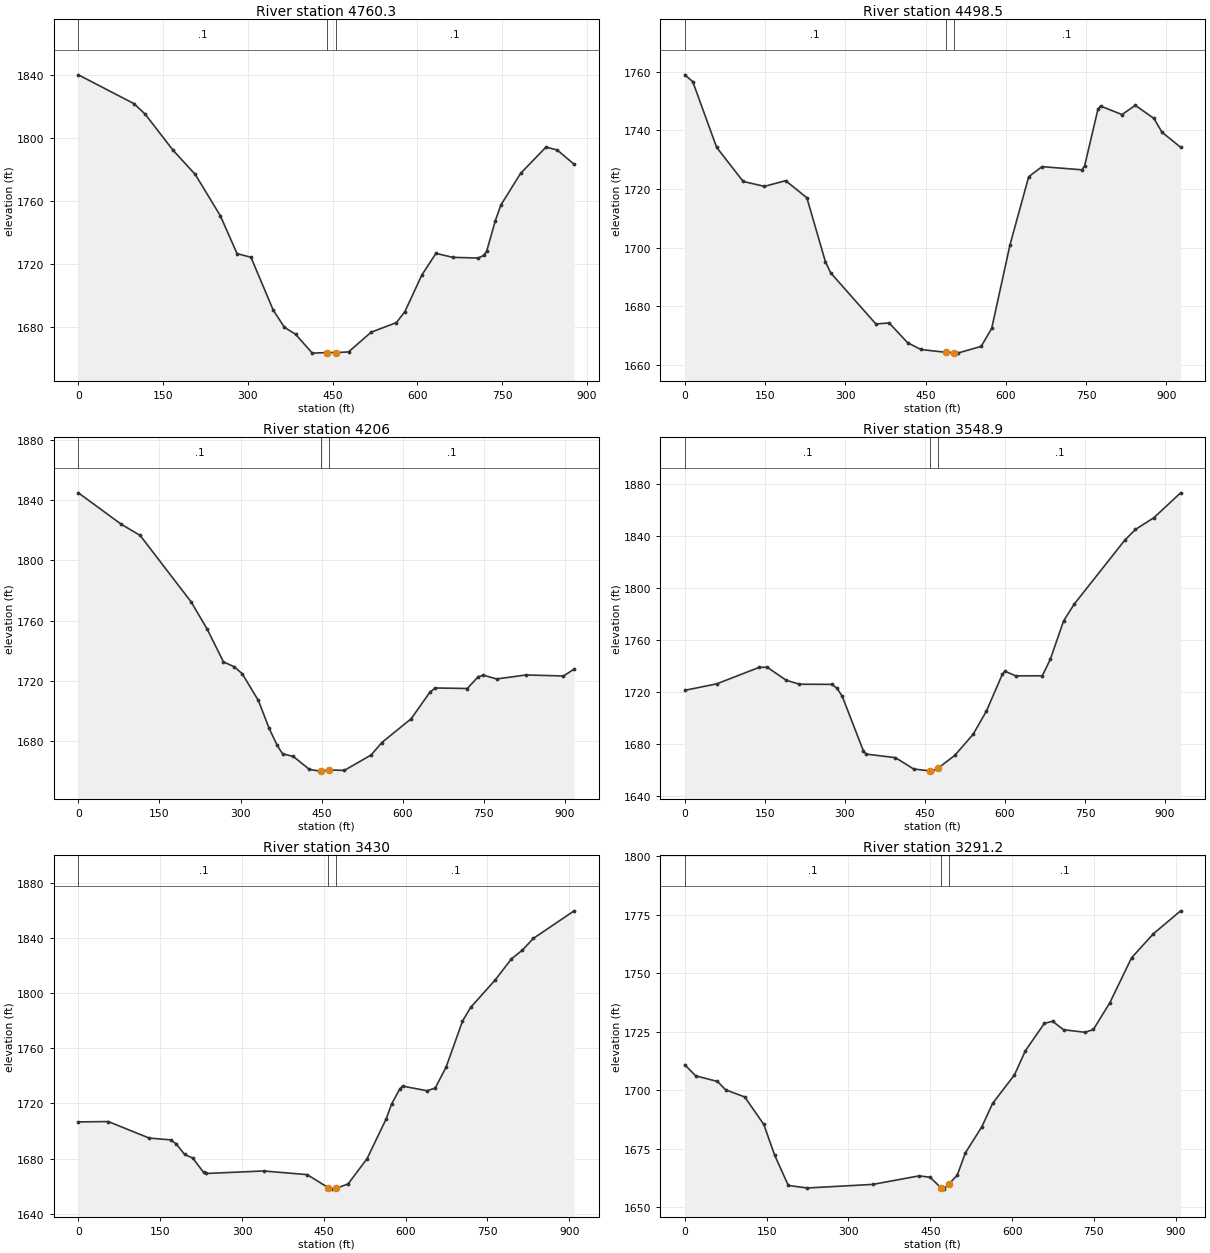
Type RM Length L Ch R = 1 ,4760.3  ,262.3,261.8,260.5
XS GIS Cut Line= 4
     1868829.839      227833.956     1868504.755      227949.638
     1868363.475      227994.434     1868002.079      228125.825
#Sta/Elev= 30
       0 1840.03    98.6 1821.76   118.3 1815.14   167.6  1792.3     207 1776.93
   251.4 1750.77     281 1726.79   305.6 1724.46     345 1691.05   364.8 1680.14
   384.6 1675.69   414.2 1663.75     441 1664.13     456 1664.06   478.4 1664.53
   518.2 1676.96   563.2 1683.11   578.2 1690.08   608.1  1713.2   633.1 1726.94
   663.1  1724.4     708 1724.01     718  1725.7     723 1728.41     738 1747.38
     748  1757.5   782.9 1777.58   827.9 1794.24   847.8 1792.44   877.8 1783.34
#Mann= 3 , 0 , 0
       0      .1       0     441    .045       0     456      .1       0
Bank Sta=441,456
XS Rating Curve= 0 ,0
Exp/Cntr=0.3,0.1

Type RM Length L Ch R = 1 ,4498.5  ,282.3,292.4,303.4
XS GIS Cut Line= 4
     1868788.367      227657.336      1868381.72      227721.695
      1868196.43      227786.546     1867878.787      227758.194
#Sta/Elev= 30
       0  1758.9    14.9 1756.58    59.5  1734.2   109.1 1722.58   148.8  1720.9
   188.5 1722.84   228.2 1717.02   262.9 1695.21   272.8 1691.42   357.2 1674.02
     382 1674.37   416.6 1667.63   441.2 1665.33   487.4 1664.38   502.4 1664.25
   509.9 1664.09     554 1666.38   573.7  1672.5     608 1701.04   642.9 1724.19
   667.8 1727.62   742.6 1726.54   747.5 1727.91   772.5 1747.31   777.4 1748.25
   817.3 1745.36   842.2 1748.51   877.1 1744.03     892 1739.36   926.9 1734.22
#Mann= 3 , 0 , 0
       0      .1       0   487.4    .045       0   502.4      .1       0
Bank Sta=487.4,502.4
XS Rating Curve= 0 ,0
Exp/Cntr=0.3,0.1

Type RM Length L Ch R = 1 ,4206    ,671.6,657.2,642.7
XS GIS Cut Line= 4
     1868780.093      227423.378     1868359.485      227462.289
     1868226.076      227449.319     1867888.849      227577.169
#Sta/Elev= 30
       0 1844.79    79.5 1823.94   114.3 1816.58   208.7 1772.48   238.5 1754.33
   268.4 1732.77   288.2 1729.53   303.1 1724.94     333 1707.16   352.8 1688.83
   367.7 1677.49   377.7 1671.87   397.6 1670.07   427.4 1661.49   447.2 1660.35
   449.5 1660.36   464.5 1661.18   491.9 1660.82   541.6 1671.04   561.4 1679.31
   615.7 1695.09   650.3 1712.67   660.2 1715.46   719.5 1715.11   739.2 1722.82
   749.1 1723.95   773.8 1721.44   828.2 1724.09   897.3  1723.4   917.1 1727.95
#Mann= 3 , 0 , 0
       0      .1       0   449.5    .045       0   464.5      .1       0
Bank Sta=449.5,464.5
XS Rating Curve= 0 ,0
Exp/Cntr=0.3,0.1

Type RM Length L Ch R = 1 ,3548.9  ,120.2,118.9,117.6
XS GIS Cut Line= 4
     1868681.843       226571.25     1868344.662      226795.246
     1868250.164      226852.686     1867871.055      227018.282
#Sta/Elev= 30
       0 1721.52      60 1726.52   139.9 1739.29   154.9 1739.17   189.9 1729.29
   214.9 1726.21   274.9 1726.11   284.9 1723.31   294.9 1717.02   334.8 1674.79
   339.8 1672.45   394.8  1669.7   428.8 1660.99   459.4  1659.5   462.5 1659.34
   474.4 1661.57   505.8 1671.42   540.3 1687.68   565.2 1705.55   595.1 1733.94
   600.1 1736.21   620.1 1732.67   669.9  1732.7   684.9 1745.37   709.8 1774.92
   729.7 1787.85   824.4 1837.04   844.4 1845.32   879.2  1854.4   929.1  1873.5
#Mann= 3 , 0 , 0
       0      .1       0   459.4    .045       0   474.4      .1       0
Bank Sta=459.4,474.4
XS Rating Curve= 0 ,0
Exp/Cntr=0.3,0.1

Type RM Length L Ch R = 1 ,3430    ,135.5,138.8,142
XS GIS Cut Line= 2
     1868613.396       226459.96     1867867.116      226978.803
#Sta/Elev= 30
       0 1706.55    54.9 1706.78   129.8 1694.83   169.8 1693.49   179.8 1690.41
   194.8 1682.99   209.8 1680.31   229.7  1669.9   234.7 1669.15   339.6 1670.98
   419.5 1668.32     458  1658.9   464.4 1657.81     473 1658.53   494.4 1661.51
   529.4 1679.99   564.3 1708.71   574.3 1719.56   589.3 1730.46   594.3 1732.49
   639.2 1729.13   654.2 1731.07   674.2 1746.29   704.2 1779.56   719.1 1789.51
   764.1 1809.42     794 1824.75     814 1831.03     834 1839.54   908.9 1859.55
#Mann= 3 , 0 , 0
       0      .1       0     458    .045       0     473      .1       0
Bank Sta=458,473
XS Rating Curve= 0 ,0
Exp/Cntr=0.3,0.1

Type RM Length L Ch R = 1 ,3291.2  ,270.3,271.7,273.2
XS GIS Cut Line= 2
     1868576.851      226404.532     1867762.871      226808.967
#Sta/Elev= 30
       0 1710.83      20 1706.14    59.9 1703.73    74.9 1700.16   109.9 1697.12
   144.8 1685.39   164.8 1672.22   189.8 1659.32   224.7 1658.26   344.6 1659.79
   429.5 1663.43   449.5 1662.84   469.9  1658.3   474.4 1657.77   484.9 1660.16
   499.4 1663.69   514.4 1673.29   544.4 1684.34   564.3 1694.39   604.3 1706.53
   624.3 1716.84   659.2 1728.56   674.2 1729.42   694.2 1725.82   734.1 1724.71
   749.1 1725.95   779.1 1737.32     819 1756.55     859 1766.79   908.9 1776.58
#Mann= 3 , 0 , 0
       0      .1       0   469.9    .045       0   484.9      .1       0
Bank Sta=469.9,484.9
XS Rating Curve= 0 ,0
Exp/Cntr=0.3,0.1

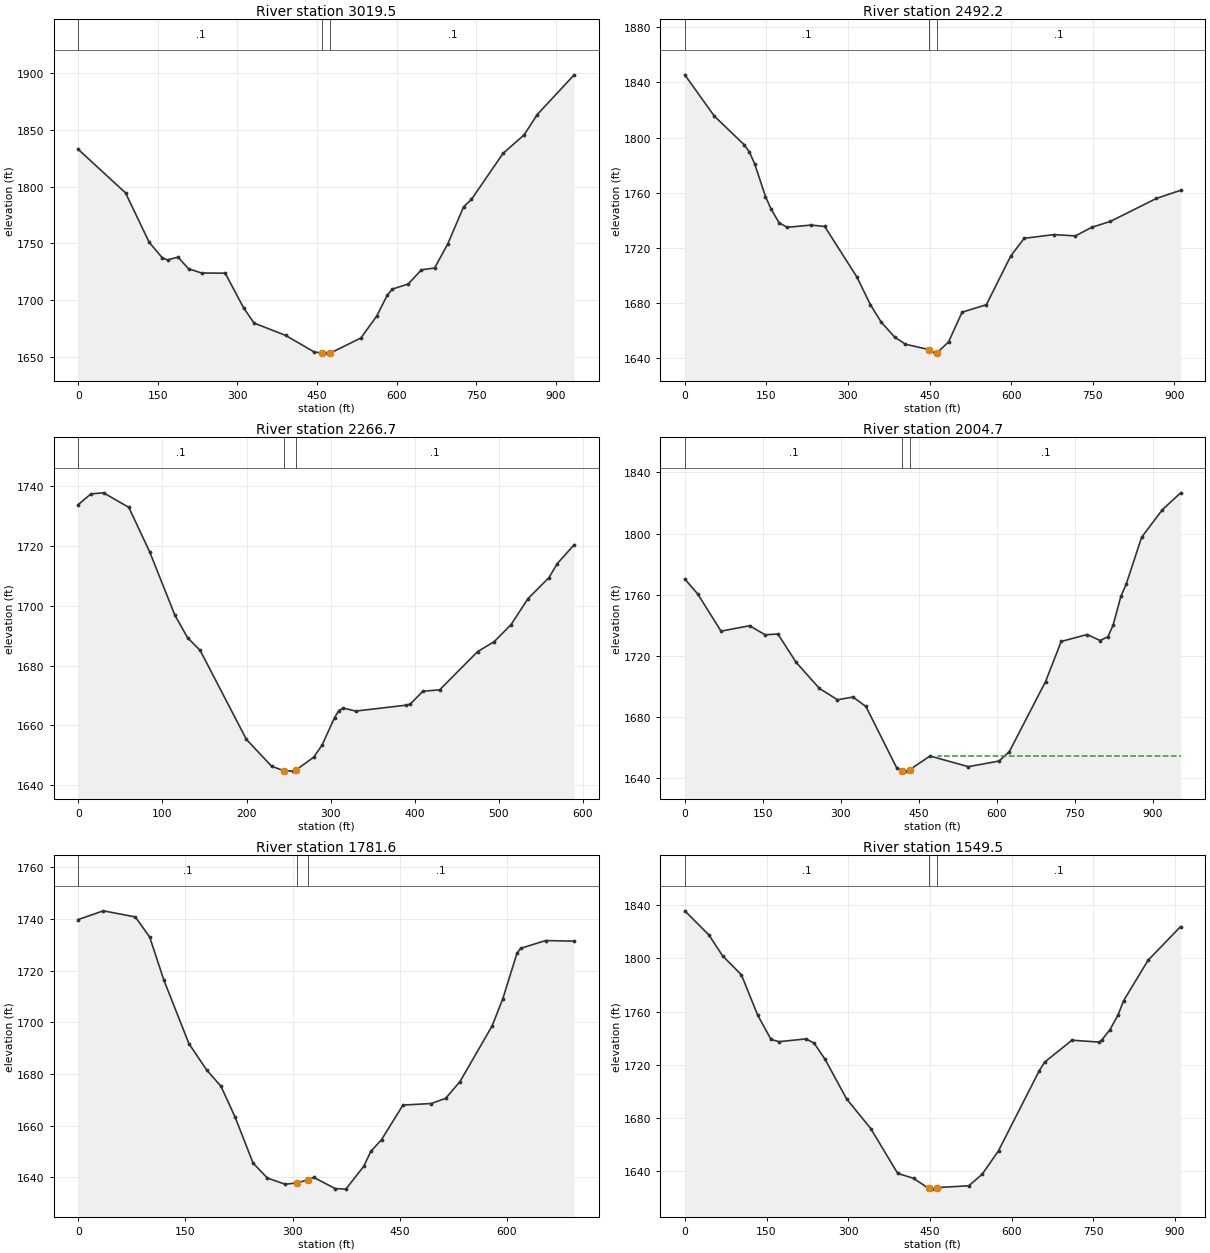
Type RM Length L Ch R = 1 ,3019.5  ,529.7,527.3,524.9
XS GIS Cut Line= 4
     1868500.305       226081.88     1868179.754      226330.169
     1868066.727      226376.491     1867664.509      226439.058
#Sta/Elev= 30
       0 1832.64      89 1794.46   133.5 1751.03   158.2 1737.36   168.1  1735.5
   187.9 1737.93   207.7 1727.74   232.4 1723.96   276.9 1723.84   311.5 1693.39
   331.3 1679.92   390.6 1669.12   444.6 1654.55   460.1 1653.52     469 1653.49
   475.1 1653.58   532.6 1666.82   562.4 1685.99   582.2 1704.28   592.2 1709.86
   621.9 1714.29   646.8 1726.79   671.6 1728.36   696.4 1749.52   726.2 1782.12
   741.1 1788.74   800.6 1829.16   840.4 1845.48   865.2 1863.39   934.7 1898.29
#Mann= 3 , 0 , 0
       0      .1       0   460.1    .045       0   475.1      .1       0
Bank Sta=460.1,475.1
XS Rating Curve= 0 ,0
Exp/Cntr=0.3,0.1

Type RM Length L Ch R = 1 ,2492.2  ,226.5,225.5,224.4
XS GIS Cut Line= 3
     1868339.794      225696.646     1867988.905      225831.739
     1867517.392      226086.205
#Sta/Elev= 30
       0 1845.52    54.4 1815.52   108.8 1794.95   118.7 1789.67   128.6 1780.81
   148.4 1757.24   158.3 1748.44   173.2 1738.31     188 1734.89   232.5 1736.54
   257.3  1735.5   316.6 1698.79   341.4 1678.72   361.2 1666.14   385.9 1655.27
   405.8 1650.08   448.7 1646.25   460.3 1643.63   463.7 1643.73   485.1 1651.84
   509.9 1673.32   554.6 1678.76   599.2 1713.95     624 1726.89   678.6 1729.62
   718.3 1728.68   748.1 1734.86   782.8 1739.22   867.1 1755.83   911.8 1761.75
#Mann= 3 , 0 , 0
       0      .1       0   448.7    .045       0   463.7      .1       0
Bank Sta=448.7,463.7
XS Rating Curve= 0 ,0
Exp/Cntr=0.3,0.1

Type RM Length L Ch R = 1 ,2266.7  ,266.2,262,257.9
XS GIS Cut Line= 2
     1868074.061      225533.655     1867558.395      225819.254
#Sta/Elev= 30
       0 1733.91      15 1737.47      30 1737.82      60 1732.97    84.9 1718.01
   114.9 1696.82   129.9 1689.36   144.9 1685.08   199.8 1655.34   229.8 1646.36
     244 1644.88   254.8 1644.72     259 1645.15   279.8 1649.37   289.7 1653.38
   304.7 1662.66   309.7 1664.96   314.7 1665.84   329.7 1664.81   389.6 1666.78
   394.6 1667.13   409.6 1671.45   429.6 1671.91   474.6 1684.68   494.6 1688.08
   514.5 1693.74   534.5 1702.39   559.5 1709.44   569.5 1714.16   589.5 1720.45
#Mann= 3 , 0 , 0
       0      .1       0     244    .045       0     259      .1       0
Bank Sta=244,259
XS Rating Curve= 0 ,0
Exp/Cntr=0.3,0.1

Type RM Length L Ch R = 1 ,2004.7  ,208.1,223.1,238.1
XS GIS Cut Line= 4
     1868197.699      225339.958      1867825.85      225374.073
     1867636.855      225538.981     1867370.499      225733.353
#Sta/Elev= 30
       0 1770.24    24.9 1760.42    69.7  1736.1   124.5 1739.66   154.3 1733.76
   179.2  1734.2   214.1 1715.75   258.9 1698.63   293.8 1691.18   323.6 1692.99
   348.5 1686.79   407.8 1646.56   418.2 1644.75   427.5 1644.48   433.2 1645.53
   471.8 1654.38   545.6  1647.4   604.6 1651.09   624.2 1657.12   694.2 1703.14
   724.2 1729.34   774.1  1733.9   799.1 1729.98   814.1 1732.43   824.1 1740.04
   839.1 1758.96   849.1 1766.67     879 1797.59     919 1815.63     954 1826.64
#Mann= 3 , 0 , 0
       0      .1       0   418.2    .045       0   433.2      .1       0
#XS Ineff= 2 , 0
                          486.27         1654.09
Permanent Ineff=
       F       F
Bank Sta=418.2,433.2
XS Rating Curve= 0 ,0
Exp/Cntr=0.3,0.1

Type RM Length L Ch R = 1 ,1781.6  ,232.8,232.1,231.4
XS GIS Cut Line= 2
     1868058.195      225181.944     1867365.351      225229.544
#Sta/Elev= 30
       0 1739.75      35 1743.11    79.9 1740.74    99.9 1732.98   119.9 1716.26
   154.9 1691.74   179.9 1681.49   199.8 1675.25   219.8 1663.19   244.8 1645.52
   264.8 1639.74   289.8 1637.35   306.8 1637.89   321.8  1639.1   329.8    1640
   359.7 1635.68   374.7 1635.46   399.7 1644.27   409.7 1650.05   424.7 1654.61
   454.7 1667.97   494.6 1668.58   514.6  1670.6   534.6 1677.08   579.6 1698.59
   594.6 1709.14   614.5 1726.76   619.5 1728.59   654.5 1731.61   694.5 1731.38
#Mann= 3 , 0 , 0
       0      .1       0   306.8    .045       0   321.8      .1       0
Bank Sta=306.8,321.8
XS Rating Curve= 0 ,0
Exp/Cntr=0.3,0.1

Type RM Length L Ch R = 1 ,1549.5  ,261.5,261.7,261.4
XS GIS Cut Line= 4
     1868206.401      224929.392     1867807.321      224966.436
     1867677.618      224979.406     1867298.797      224995.631
#Sta/Elev= 30
       0 1835.79    44.5 1817.57    69.3 1801.96   103.9 1787.69   133.6 1757.58
   158.3 1739.04   173.2 1737.39   222.7 1739.48   237.5 1736.22   257.3 1724.28
   296.9 1694.43   341.4 1672.01   390.9 1638.28   420.1 1634.61   447.7 1627.01
   453.9 1626.48   462.7 1627.64   521.5 1629.02   546.1 1637.76     576 1655.41
   650.9 1715.66   660.9 1722.12   710.8 1738.47   760.6 1737.08   765.6 1738.66
   780.6 1746.45   795.6 1757.62   805.5 1768.12   850.4 1798.55   910.3 1823.98
#Mann= 3 , 0 , 0
       0      .1       0   447.7    .045       0   462.7      .1       0
Bank Sta=447.7,462.7
XS Rating Curve= 0 ,0
Exp/Cntr=0.3,0.1

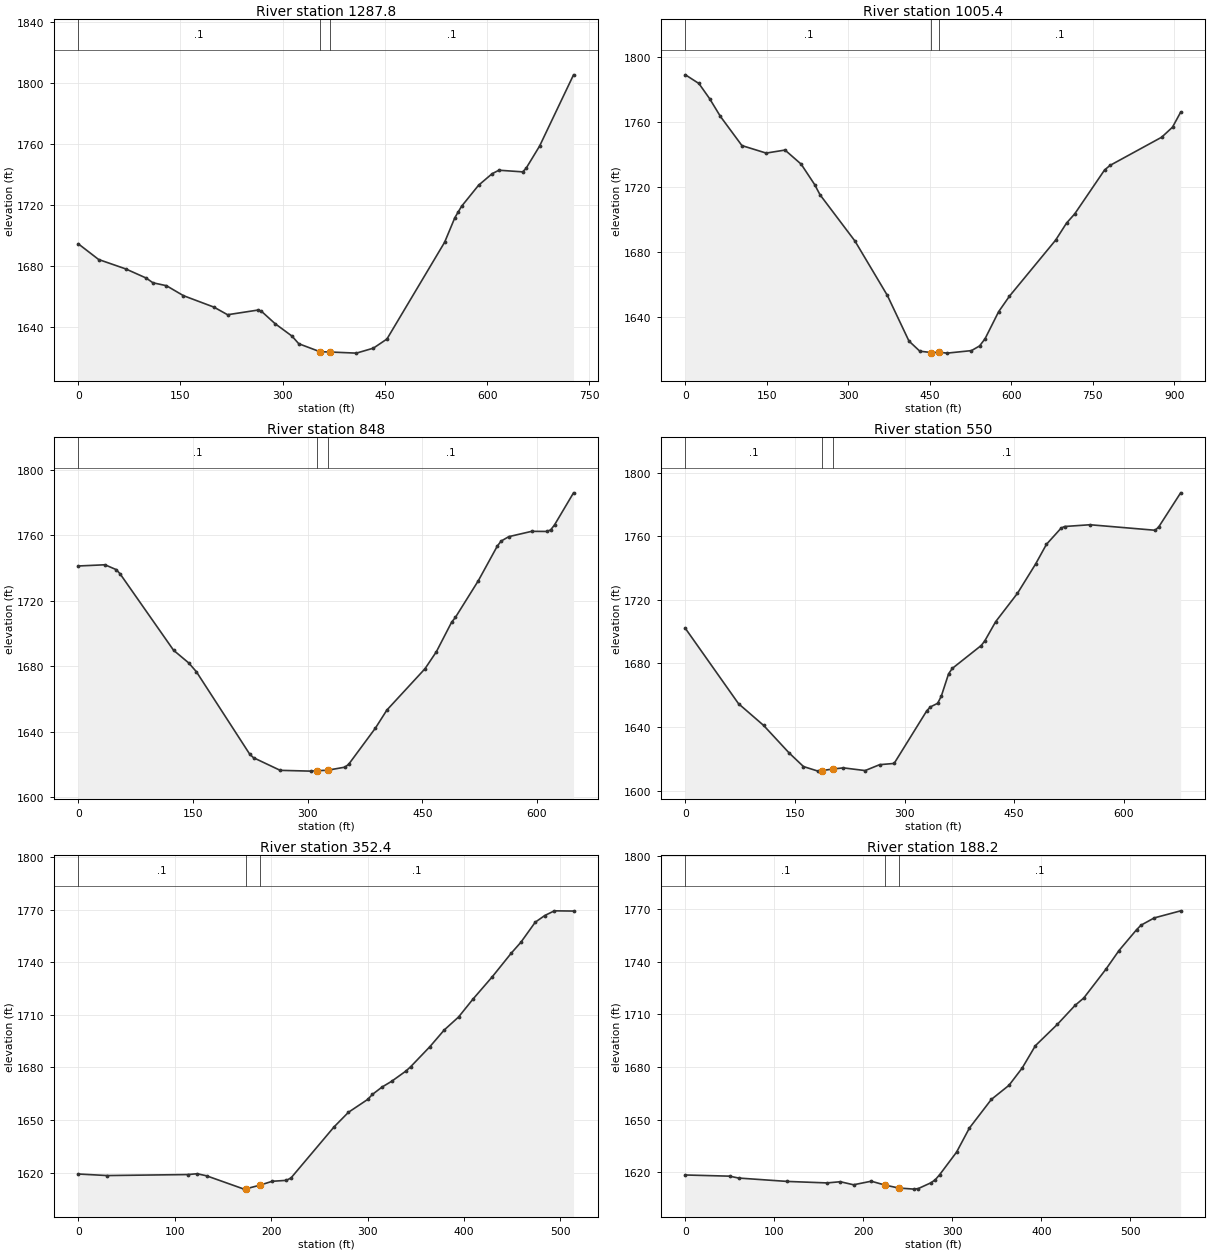
Type RM Length L Ch R = 1 ,1287.8  ,279.4,282.5,286
XS GIS Cut Line= 2
     1868047.617      224682.145     1867325.685      224766.767
#Sta/Elev= 30
       0 1694.64    29.9 1684.35    69.7 1678.18    99.6 1672.21   109.5  1669.1
   129.4 1667.18   154.3 1660.65   199.1 1653.13   219.1 1648.14   263.9 1651.22
   268.8 1650.42   288.8  1642.3   313.6 1634.15   323.6 1629.12   354.7 1623.89
   369.7 1623.69   408.2 1622.96   433.1 1626.22     453  1632.2   537.7 1695.69
   552.6 1711.69   557.6 1715.54   562.6 1719.28   587.5 1733.06   607.4 1740.63
   617.4 1742.92   652.2 1741.84   657.2 1744.13   677.1 1758.78   726.9 1805.48
#Mann= 3 , 0 , 0
       0      .1       0   354.7    .045       0   369.7      .1       0
Bank Sta=354.7,369.7
XS Rating Curve= 0 ,0
Exp/Cntr=0.3,0.1

Type RM Length L Ch R = 1 ,1005.4  ,154.8,157.4,160
XS GIS Cut Line= 3
     1868110.434      224490.423     1867725.794      224453.183
      1867201.38      224430.368
#Sta/Elev= 30
       0 1788.84    24.8 1783.52    44.6 1774.19    64.4 1763.32     104 1745.43
   148.6 1740.83   183.3 1742.69     213 1734.04   237.8 1721.52   247.7 1715.27
   312.1 1686.83   371.6 1653.53   411.4 1625.52   431.4 1619.29   452.4 1618.48
   467.4 1618.66   481.4 1618.11   526.4 1619.65   541.4 1622.53   551.4 1626.92
   576.4 1643.52   596.4 1653.08   681.4 1687.47   701.4  1697.9   716.4 1703.52
   771.4 1730.48   781.4 1733.27   876.4 1750.56   896.4 1756.72   911.4 1765.94
#Mann= 3 , 0 , 0
       0      .1       0   452.4    .045       0   467.4      .1       0
Bank Sta=452.4,467.4
XS Rating Curve= 0 ,0
Exp/Cntr=0.3,0.1

Type RM Length L Ch R = 1 ,848     ,301.6,298,294.4
XS GIS Cut Line= 2
     1867976.217      224343.657     1867336.263      224243.168
#Sta/Elev= 30
       0 1741.17    34.9 1741.91    49.8 1738.91    54.8 1736.28   124.6 1689.69
   144.5 1681.91   154.5 1676.54   224.2 1626.21   229.2 1624.02   264.1 1616.31
     304 1615.83   311.6 1616.03   326.6 1616.42   348.8 1618.26   353.8 1620.09
   388.7 1642.16   403.6 1653.12   453.5  1678.4   468.4  1688.8   488.3 1706.81
   493.3 1709.78   523.2 1732.13   548.1 1753.35   553.1  1756.4   563.1 1759.09
     593 1762.34   612.9 1762.27   617.9 1763.24   622.9 1766.25   647.8 1785.87
#Mann= 3 , 0 , 0
       0      .1       0   311.6    .045       0   326.6      .1       0
Bank Sta=311.6,326.6
XS Rating Curve= 0 ,0
Exp/Cntr=0.3,0.1

Type RM Length L Ch R = 1 ,550     ,213.7,197.6,181.4
XS GIS Cut Line= 3
     1867941.213       224047.19     1867857.349       224023.31
     1867266.696      224020.962
#Sta/Elev= 30
       0 1702.03    72.7 1654.66     107 1641.01   141.8 1623.73   161.6 1615.09
   181.5 1612.21   187.5  1612.6   202.5 1613.57   216.2 1614.26     246 1612.56
   265.9 1616.28   285.7 1617.05   330.4 1650.21   335.4 1652.65   345.3 1654.92
   350.3 1659.46   360.2 1673.44   365.2 1676.83   404.9 1691.29   409.8 1694.21
   424.7 1706.31   454.5 1724.14   479.3 1742.56   494.2    1755   514.1 1765.11
     519 1766.21   553.8 1767.32   643.1 1763.84   648.1  1766.1   677.9 1787.41
#Mann= 3 , 0 , 0
       0      .1       0   187.5    .045       0   202.5      .1       0
Bank Sta=187.5,202.5
XS Rating Curve= 0 ,0
Exp/Cntr=0.3,0.1

Type RM Length L Ch R = 1 ,352.4   ,151.3,164.2,171.9
XS GIS Cut Line= 4
     1867832.082      223809.922     1867773.969      223771.316
     1867662.795      223865.814     1867383.633      223969.816
#Sta/Elev= 30
       0  1619.2    29.9 1618.32   113.5 1618.89   123.3 1619.35     133 1618.18
   171.9 1610.58   173.4  1610.7   188.4 1612.84   201.1 1615.05   215.7 1615.58
   220.6 1616.96   265.3  1646.1   280.2 1654.41   300.1 1661.72     305 1664.57
     315 1668.78   324.9 1672.04   339.8 1677.91   344.8 1680.44   364.6 1691.79
   379.5 1701.32   394.4 1708.74   409.3 1718.92   429.2 1731.57     449 1745.12
     459 1751.33   473.9 1762.78   483.8 1766.59   493.7 1769.26   513.6 1769.13
#Mann= 3 , 0 , 0
       0      .1       0   173.4    .045       0   188.4      .1       0
Bank Sta=173.4,188.4
XS Rating Curve= 0 ,0
Exp/Cntr=0.3,0.1

Type RM Length L Ch R = 1 ,188.2   ,187.3,188.2,194.2
XS GIS Cut Line= 4
     1867818.165        223782.1     1867622.479      223695.736
     1867524.052       223733.07     1867325.257      223863.133
#Sta/Elev= 30
       0 1618.37    49.7  1617.7    59.7 1616.63   114.4  1614.7   159.2 1613.85
   174.1 1614.53     189 1612.79   208.9 1614.82   224.6 1612.59   239.6 1610.96
     257 1610.31   261.8 1610.64   276.1 1613.95   280.9 1615.69   285.7 1618.48
   304.8  1631.4   319.2 1645.11   343.9 1661.45   363.7 1669.48   378.6 1679.37
   393.4 1692.07   418.2 1704.28     438 1715.05   447.8 1719.26   472.6 1735.62
   487.4 1746.32   507.2 1758.22   512.2 1760.78     527 1764.91   556.7 1768.95
#Mann= 3 , 0 , 0
       0      .1       0   224.6    .045       0   239.6      .1       0
Bank Sta=224.6,239.6
XS Rating Curve= 0 ,0
Exp/Cntr=0.3,0.1

Chan Stop Cuts=-1
Use User Specified Reach Order=0